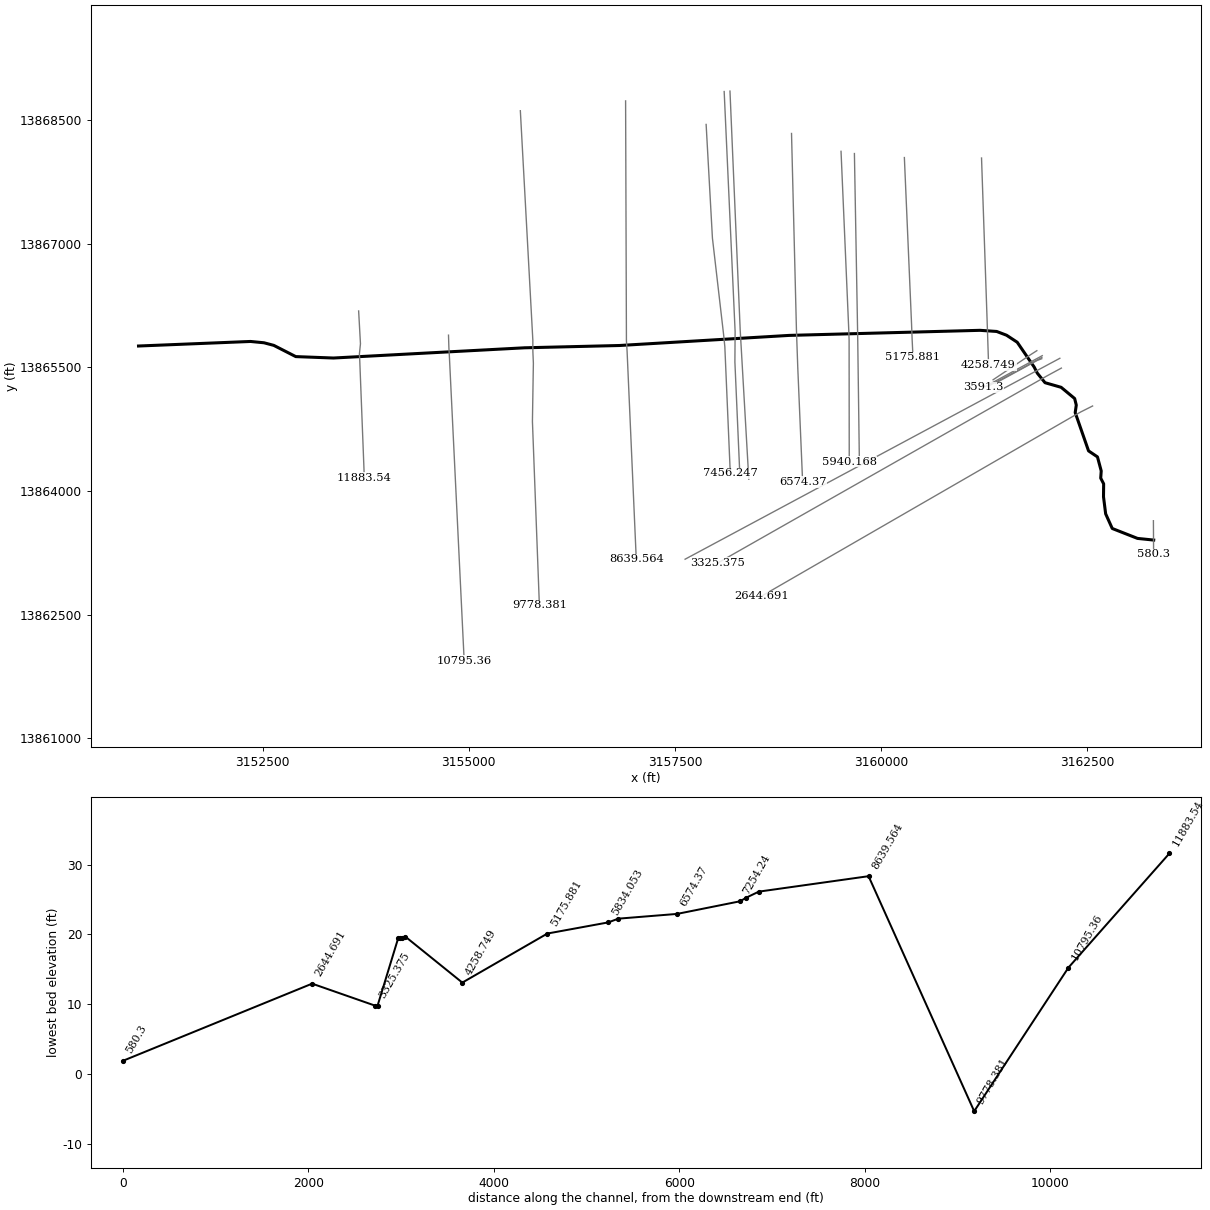
--- P114-00-00.prj (project) ---

Proj Title=P114-00-00
Current Plan=p01
Default Exp/Contr=.3,.1
English Units
Geom File=g01
Flow File=f03
Flow File=f01
Plan File=p14
Plan File=p01
Y Axis Title=Elevation
X Axis Title(PF)=Main Channel Distance
X Axis Title(XS)=Station
BEGIN DESCRIPTION:
& RHCFCD Unit P114-00-00
(Flood Hazard, Flood Way) Model
10, 2, 1, .2% Event
Filename P114-00-00.prj
Prepared by:  Jones & Carter, Inc.  	Date:  7-10-02
Reviewed by:			Date:
STATUS (Final RAS)
END DESCRIPTION:
DSS Export Rating Curves= 0
DSS Export Rating Curve Sorted= 0
DSS Export Volume Flow Curves= 0
DXF OffsetX= 0
DXF OffsetY= 0
DXF ScaleX= 1
DXF ScaleY= 10

--- P114-00-00.p01 (plan) ---

Plan Title=Floodway
Version=Version 3.0.1  Mar 2001
Short Identifier=Floodway0607
Geom File=g01
Flow File=f01
Subcritical Flow
K Sum by GR= 0
Std Step Tol= 0.01
Critical Tol= 0.01
Num of Std Step Trials= 20
Max Error Tol= 0.3
Flow Tol Ratio= 0.001
Split Flow NTrial= 30
Split Flow Tol= 0.02
Split Flow Ratio= 0.02
Log Output Level= 0
Friction Slope Method= 1
Unsteady Friction Slope Method= 2
Parabolic Critical Depth
Global Vel Dist= 0 , 0 , 0
Global Log Level= 0
CheckData=True
Encroach Param=-1 ,0,0, 2
Encroach River=P1140000
Encroach Reach=1
Encroach Node=14614.86
       1  227.78  294.75
Encroach Node=14517.75
       1  871.02  976.09
Encroach Node=14292.71
       1  891.43  963.39
Encroach Node=13931.6
       1  871.48 1822.07
Encroach Node=13888.14
       1  885.92 1478.72
Encroach Node=13593.44
       1  902.97  949.06
Encroach Node=13276.85
       1  880.09  963.35
Encroach Node=12695.9
       1 1094.63 1146.15
Encroach Node=12036.8
       1  221.78  311.91
Encroach Node=11935.8
       1  221.78  592.26
Encroach Node=11883.54
       1  484.49  592.26
Encroach Node=10795.36
       1  148.65  261.25
Encroach Node=9778.381
       1 2803.54 2948.92
Encroach Node=8639.564
       1 2884.08 3017.74
Encroach Node=7456.247
       1 2546.99 2685.52
Encroach Node=7378.25
       1 2546.99 3083.73
Encroach Node=7322.337
       1 2941.53 3083.73
Encroach Node=7254.24
       1 2942.49 3094.51
Encroach Node=6574.37
       1 2376.17 2532.98
Encroach Node=5940.168
       1 2144.81 2303.21
Encroach Node=5864.17
       1  2124.4 2303.21
Encroach Node=5834.053
       1  2124.4 2259.23
Encroach Node=5175.881
       1 2063.25 2209.23
Encroach Node=4258.749
       1 1973.42 2148.32
Encroach Node=3645.18
       1   74.89  174.36
Encroach Node=3614.18
       1    59.3  186.26
Encroach Node=3591.3
       1    59.3  186.26
Encroach Node=3570.41
       1    59.3  186.26
Encroach Node=3549.434
       1    59.3  186.26
Encroach Node=3448.434
       1    59.3  314.46
Encroach Node=3349.25
       1  197.37  314.46
Encroach Node=3325.375
       1  197.37  314.46
Encroach Node=2644.691
       1  167.33  293.07
Encroach Node=580.3
       1  204.92  340.64
Encroach Reach=P114-00-00_0006
Encroach Node=11883.54
       1  484.49  592.26
Encroach Node=10795.36
       1  148.65  261.25
Encroach Node=9778.381
       1 2803.54 2948.92
Encroach Node=8639.564
       1 2884.08 3017.74
Encroach Node=7456.247
       1 2546.99 2685.52
Encroach Node=7378.25
       1 2546.99 3083.73
Encroach Node=7322.337
       1 2941.53 3083.73
Encroach Node=7254.24
       1 2942.49 3094.51
Encroach Node=6574.37
       1 2376.17 2532.98
Encroach Node=5940.168
       1 2144.81 2303.21
Encroach Node=5864.17
       1  2124.4 2303.21
Encroach Node=5834.053
       1  2124.4 2259.23
Encroach Node=5175.881
       1 2063.25 2209.23
Encroach Node=4258.749
       1 1973.42 2148.32
Encroach Node=3645.18
       1   74.89  174.36
Encroach Node=3614.18
       1    59.3  186.26
Encroach Node=3591.3
       1    59.3  186.26
Encroach Node=3570.41
       1    59.3  186.26
Encroach Node=3549.434
       1    59.3  186.26
Encroach Node=3448.434
       1    59.3  314.46
Encroach Node=3349.25
       1  197.37  314.46
Encroach Node=3325.375
       1  197.37  314.46
Encroach Node=2644.691
       1  167.33  293.07
Encroach Node=580.3
       1  204.92  340.64
Computation Interval=1HOUR
Output Interval=1HOUR
Run HTab= 0
Run UNet= 0
Run PostProcess= 0
UNET Theta= 1
UNET ZTol= 0.02
UNET ZSATol= 0.1
UNET MxIter= 20
UNET MaxInSteps= 20
UNET DtIC= 0
UNET DtMin= 0
UNET MaxCRTS= 20
UNET WFStab= 2
UNET SFStab= 1
UNET WFX= 1
UNET SFX= 1
UNET Convert EG Bridges=-1
UNET Use Existing IB Tables=-1
Instantaneous Interval=1HOUR
Write IC File= 0
Write Velocity= 0
Write Detailed= 0

--- P114-00-00.p14 (plan) ---

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Plan Title=FEMA Effective June 2007
Short Identifier=FEMAeff0607
Geom File=g01
Flow File=f03
Encroach Param=-1 ,0,0, 0

--- P114-00-00.f01 (steady flow) ---

Flow Title=Floodway
Version=Version 3.0.1  Mar 2001
Number of Profiles= 2
Profile Names=1PCT_100yr, 1PCTFloodway_100yrFW
River Rch & RM=P1140000,P114-00-00_0006               ,12695.9
     769     769
River Rch & RM=P1140000,P114-00-00_0006               ,12036.8
     859     859
River Rch & RM=P1140000,P114-00-00_0006               ,11883.54
     859     859
River Rch & RM=P1140000,P114-00-00_0006               ,10795.36
     926     926
River Rch & RM=P1140000,P114-00-00_0006               ,9778.381
    1006    1006
River Rch & RM=P1140000,P114-00-00_0006               ,8639.564
    1097    1097
River Rch & RM=P1140000,P114-00-00_0006              ,7456.247
    1170    1170
River Rch & RM=P1140000,P114-00-00_0006             ,6574.37
    1170    1170
River Rch & RM=P1140000,P114-00-00_0006               ,5940.168
    2422    2422
River Rch & RM=P1140000,P114-00-00_0006               ,5834.053
    2422    2422
River Rch & RM=P1140000,P114-00-00_0006               ,5175.881
    2540    2540
River Rch & RM=P1140000,P114-00-00_0006               ,4258.749
    2714    2714
River Rch & RM=P1140000,P114-00-00_0006              ,3645.18
    2905    2905
River Rch & RM=P1140000,P114-00-00_0006              ,3549.434
    2905    2905
River Rch & RM=P1140000,P114-00-00_0006             ,3325.375
    3026    3026
River Rch & RM=P1140000,P114-00-00_0006               ,2644.691
    3435    3435
Boundary for River Rch & Prof#=P1140000,P114-00-00_0006              , 1
Up Type= 0
Dn Type= 3
Dn Slope=.002
Boundary for River Rch & Prof#=P1140000,P114-00-00_0006             , 2
Up Type= 0
Dn Type= 3
Dn Slope=.002
DSS Import GetInterval= 0
DSS Import GetPeak= 0
DSS Import FillOption= 0

--- P114-00-00.f03 (steady flow) ---

Flow Title=FEMA Effective June 2007
Version=Version 3.0.1  Mar 2001
Number of Profiles= 4
Profile Names=10PCT_10yr, 2PCT_50yr, 1PCT_100yr, 0.2PCT_500yr
River Rch & RM=P1140000,P114-00-00_0006           ,14614.86
     284     403     465     633
River Rch & RM=P1140000,P114-00-00_0006             ,14517.75
     297     422     487     663
River Rch & RM=P1140000,P114-00-00_0006              ,14292.71
     320     454     524     713
River Rch & RM=P1140000,P114-00-00_0006             ,13931.6
     323     458     528     719
River Rch & RM=P1140000,P114-00-00_0006              ,13888.14
     343     486     561     764
River Rch & RM=P1140000,P114-00-00_0006             ,13593.44
     365     519     598     814
River Rch & RM=P1140000,P114-00-00_0006             ,13276.85
     412     585     674     918
River Rch & RM=P1140000,P114-00-00_0006           ,12695.9
     470     667     769    1047
River Rch & RM=P1140000,P114-00-00_0006              ,12036.8
     521     744     859    1171
River Rch & RM=P1140000,P114-00-00_0006             ,11883.54
     521     744     859    1171
River Rch & RM=P1140000,P114-00-00_0006            ,10795.36
     556     801     926    1262
River Rch & RM=P1140000,P114-00-00_0006            ,9778.381
     600     870    1006    1374
River Rch & RM=P1140000,P114-00-00_0006             ,8639.564
     648     948    1097    1500
River Rch & RM=P1140000,P114-00-00_0006             ,7456.247
     686    1011    1170    1601
River Rch & RM=P1140000,P114-00-00_0006             ,6574.37
     686    1011    1170    1601
River Rch & RM=P1140000,P114-00-00_0006              ,5940.168
    1317    2077    2422    3344
River Rch & RM=P1140000,P114-00-00_0006              ,5834.053
    1317    2077    2422    3344
River Rch & RM=P1140000,P114-00-00_0006             ,5175.881
    1374    2177    2540    3509
River Rch & RM=P1140000,P114-00-00_0006               ,4258.749
    1458    2325    2714    3753
River Rch & RM=P1140000,P114-00-00_0006              ,3645.18
    1550    2487    2905    4021
River Rch & RM=P1140000,P114-00-00_0006               ,3549.434
    1550    2487    2905    4021
River Rch & RM=P1140000,P114-00-00_0006             ,3325.375
    1627    2589    3026    4200
River Rch & RM=P1140000,P114-00-00_0006             ,2644.691
    1890    2930    3435    4809
Boundary for River Rch & Prof#=P1140000,P114-00-00_0006             , 1
Up Type= 0
Dn Type= 3
Dn Slope=.002
Boundary for River Rch & Prof#=P1140000,P114-00-00_0006            , 2
Up Type= 0
Dn Type= 3
Dn Slope=.002
Boundary for River Rch & Prof#=P1140000,P114-00-00_0006             , 3
Up Type= 0
Dn Type= 3
Dn Slope=.002
Boundary for River Rch & Prof#=P1140000,P114-00-00_0006              , 4
Up Type= 0
Dn Type= 3
Dn Slope=.002
DSS Import GetInterval= 0
DSS Import GetPeak= 0
DSS Import FillOption= 0

--- P114-00-00.g01 (geometry) ---

Geom Title=P114-00-00 June 2007
Version=Version 3.0.1  Mar 2001

River Reach=P1140000        ,P114-00-00_0006
Reach XY= 30
     3150993.732    13865759.319     3152352.418    13865814.513
     3152515.576    13865798.581     3152634.547    13865767.046
     3152901.156    13865630.875     3153357.988    13865613.633
     3155676.448    13865737.613     3156827.808    13865765.483
     3158886.758    13865888.023     3161201.288    13865949.603
     3161403.816    13865935.772     3161523.579    13865890.045
     3161652.777    13865805.123     3161858.836    13865503.664
     3161896.603    13865429.772     3161990.199    13865314.281
     3162185.673    13865258.221     3162349.472    13865122.333
     3162369.279    13865042.623     3162356.236    13864951.801
     3162518.162    13864487.124     3162626.234    13864414.208
     3162671.807    13864243.635     3162665.731    13864156.829
     3162701.321    13864087.385     3162699.585    13863930.267
     3162725.627    13863723.669     3162805.636    13863545.718
     3163112.143    13863425.389      3163308.41    13863405.352

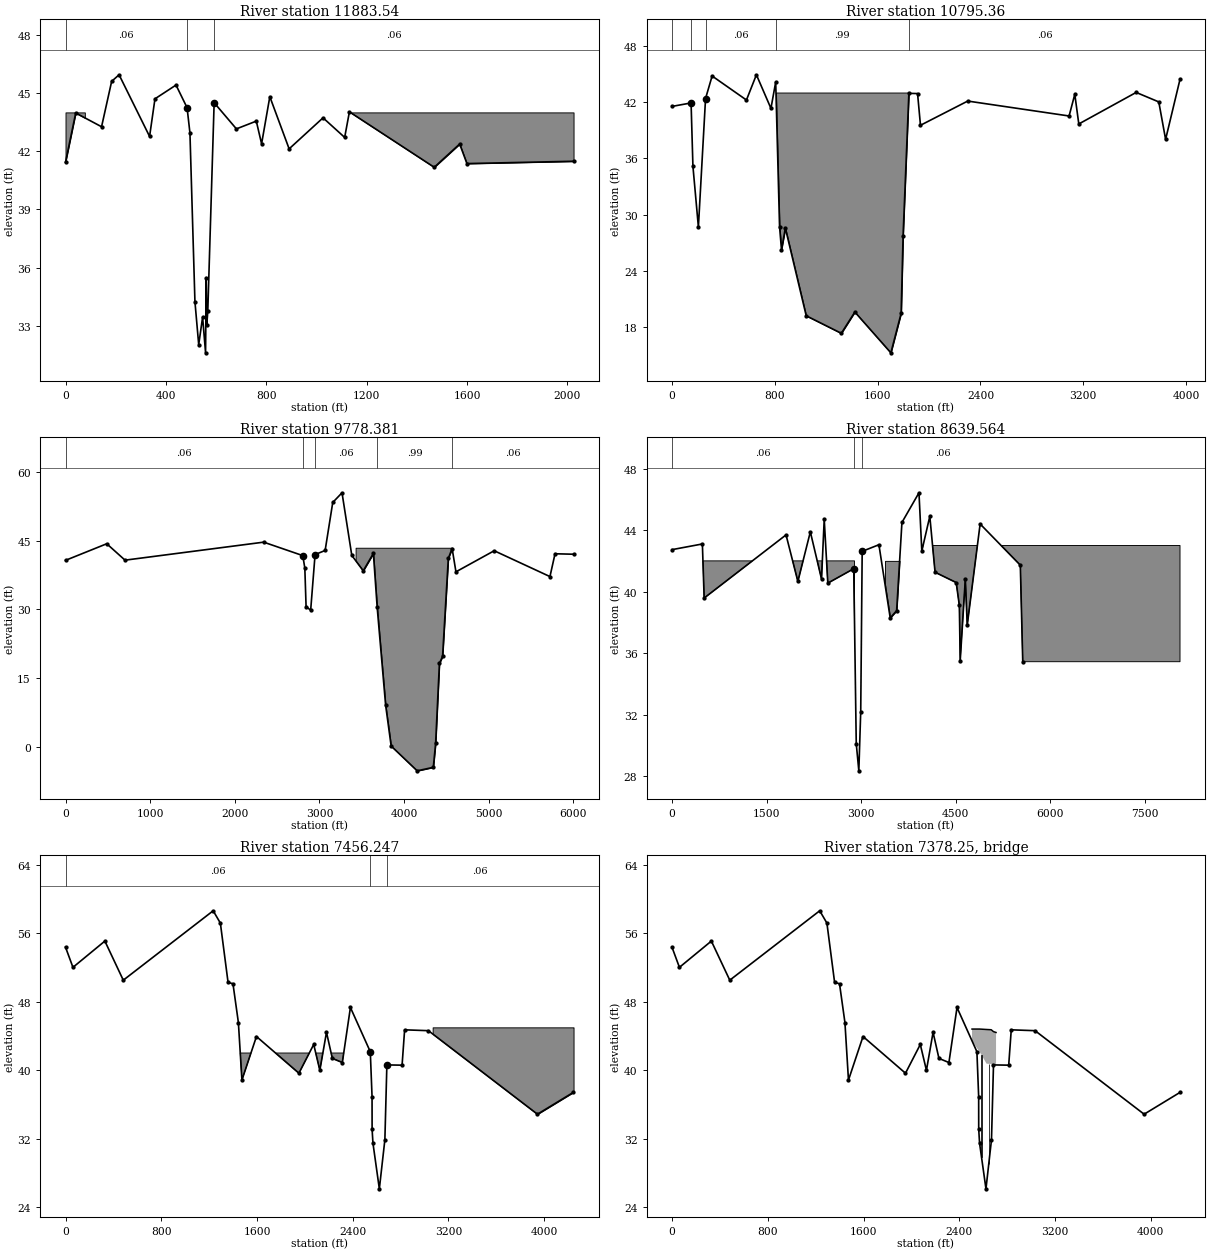
Type RM Length L Ch R = 1 ,11883.54,1087.99,1088.18,1089.02
XS GIS Cut Line= 5
      3153663.88    13866184.512     3153685.964    13865786.113
     3153673.245    13865662.991     3153677.176    13865589.367
     3153732.686    13864162.542
#Sta/Elev= 30
       0   41.43   40.71   43.97  143.68   43.26  183.85    45.6  213.45   45.94
  335.03   42.76  356.45    44.7  440.34   45.41  484.49   44.24  495.84   42.94
  515.74   34.24  530.77   32.02  546.31   33.44  558.15    31.6  560.57   35.48
  562.99   33.03     567   33.76  592.26    44.5  680.95   43.15  760.28   43.55
  781.34   42.38  814.14   44.81  891.11   42.12 1026.21   43.72 1112.39   42.71
 1131.29   44.03 1469.22   41.17 1570.64   42.37 1599.52   41.36 2024.42   41.48
#Mann= 3 ,-1 , 0
       0     .06       0  484.49    .015       0  592.26     .06       0
#Block Obstruct= 2 ,-1
       0   77.05      44 1131.29 2024.42      44
Bank Sta=484.49,592.26
XS Rating Curve= 0
Exp/Cntr=.5,.3

Type RM Length L Ch R = 1 ,10795.36,1020.21,1016.98,1012.36
XS GIS Cut Line= 5
     3154753.982    13865891.151     3154758.555    13865742.568
     3154759.203    13865731.177     3154764.311    13865641.352
     3154944.033     13861943.03
#Sta/Elev= 30
       0   41.52  148.65   41.89  163.04   35.15  205.56   28.67  261.25   42.36
  312.35   44.76  579.42    42.2  656.86   44.89  770.03   41.31  807.04   44.12
  837.08   28.71  852.09   26.25  882.13   28.56 1044.45   19.22 1317.64   17.35
 1422.77   19.62 1703.02   15.27 1783.19   19.49 1798.21   27.76 1843.26   42.91
  1910.8   42.89 1933.37   39.51 2301.14   42.09 3089.73    40.5 3134.08   42.81
 3165.23   39.65 3611.63   43.01 3787.55      42 3840.62   38.01 3952.72   44.41
#Mann= 5 ,-1 , 0
       0     .06       0  148.65     .04       0  261.25     .06       0
  807.04     .99       0 1843.26     .06       0
#Block Obstruct= 1 ,-1
  807.04 1843.26      43
Bank Sta=148.65,261.25
XS Rating Curve= 0
Exp/Cntr=.3,.1

Type RM Length L Ch R = 1 ,9778.381,1134.52,1139,1143.55
XS GIS Cut Line= 6
     3155625.424    13868613.473     3155776.906    13865832.117
     3155777.432    13865691.791     3155783.518    13865551.294
     3155772.034     13864843.92      3155856.32    13862616.371
#Sta/Elev= 30
       0   40.74  487.27   44.37  703.32   40.78 2341.62   44.72 2803.54   41.78
 2827.88   39.05  2842.6   30.64 2896.86   29.83 2948.92   42.01 3067.73    42.9
 3157.74    53.4 3267.24   55.52 3382.77   41.83 3517.79   38.45  3637.8   42.26
 3682.81   30.45 3782.55    9.06 3848.04     .12 4155.45    -5.3 4346.06   -4.53
 4373.25     .68 4418.28   18.21  4455.5   19.73 4523.36   41.17 4568.39   43.33
 4613.42   38.23 5065.57   42.84 5724.22   37.19 5784.26   42.18 6003.05   42.08
#Mann= 5 ,-1 , 0
       0     .06       0 2803.54     .04       0 2948.92     .06       0
 3682.81     .99       0 4568.39     .06       0
#Block Obstruct= 1 ,-1
 3427.78 4568.39    43.5
Bank Sta=2803.54,2948.92
XS Rating Curve= 0
Exp/Cntr=.3,.1

Type RM Length L Ch R = 1 ,8639.564,1181.19,1183.3,1187.01
XS GIS Cut Line= 4
     3156902.317    13868732.506     3156912.339    13865821.916
      3156920.33    13865696.603     3157031.731    13863170.085
#Sta/Elev= 30
       0   42.73  482.51    43.1  510.47   39.58 1809.67   43.69 1997.52   40.66
 2195.18   43.89 2372.52   40.82 2415.39   44.71 2472.35   40.55 2884.08   41.49
 2923.56   30.11 2964.55   28.34 2994.49    32.2 3017.74   42.62 3283.17   43.05
 3462.29   38.29 3564.23   38.76 3648.37    44.5 3918.63   46.43 3963.68   42.64
 4090.58    44.9 4173.88   41.26 4509.32   40.59 4559.08    39.1 4572.76   35.51
 4653.95   40.81 4684.38   37.82  4888.9    44.4 5526.44   41.72 5565.15   35.44
#Mann= 3 ,-1 , 0
       0     .06       0 2884.08     .04       0 3017.74     .06       0
#Block Obstruct= 3 ,-1
       0 2895.38      42    3380    3900      42    3900    8060      43
Bank Sta=2884.08,3017.74
XS Rating Curve= 0
Exp/Cntr=.5,.3

Type RM Length L Ch R = 1 ,7456.247,140.23,133.9,126.8
XS GIS Cut Line= 5
     3157879.175    13868447.131     3157955.504    13867068.932
     3158091.111    13865897.766     3158106.094    13865751.001
     3158172.049    13864215.793
#Sta/Elev= 30
       0   54.37   62.23   52.01  328.95   55.08  482.87   50.51 1234.02   58.62
 1294.11   57.18 1358.51   50.24 1399.37    50.1 1444.67   45.56 1474.21   38.84
 1595.67   43.93 1950.41   39.64 2074.16      43 2125.39   39.98 2180.85   44.42
 2229.88   41.37 2313.24   40.89 2380.88   47.32 2546.99   42.15 2561.65    36.9
 2562.08   33.09 2569.24   31.46  2622.6   26.13 2668.82   31.87 2685.52   40.61
 2812.61   40.58 2833.81   44.71 3032.72   44.61  3943.7   34.85 4243.45    37.4
#Mann= 3 ,-1 , 0
       0     .06       0 2546.99     .04       0 2685.52     .06       0
#Block Obstruct= 2 ,-1
       0    2380      42 3068.04 4245.46      45
Bank Sta=2546.99,2685.52
XS Rating Curve= 0
Exp/Cntr=.5,.3

Type RM Length L Ch R = 3 ,7378.25 ,,,
BEGIN DESCRIPTION:
RailRoad Bridge
END DESCRIPTION:
Bridge Culvert--1,0,-1,-1, 0
Deck Dist Width WeirC Skew NumUp NumDn MinLoCord MaxHiCord MaxSubmerge Is_Ogee
1,77,2.6,0, 6, 7, , , .95, 0, 0,0,,
 2506.17 2569.63 2627.84 2666.09 2685.52 2706.83
    44.8    44.8   44.75   44.72    44.5    44.4
   43.35   42.15   40.75   40.72   40.61   40.02
 2910.02 2934.38 2986.14 3022.67 3056.16 3077.48 3117.06
   44.54    44.8   44.75   44.72    44.5    44.4    40.2
    40.8    40.8   40.75   40.72    40.5    40.4    40.2
Pier Skew, UpSta & Num, DnSta & Num=  ,2585.76, 2 ,2978.02, 2 , 0 , 0 , 0 ,,
       2       2
    27.8      42
       2       2
    27.8      42
Pier Skew, UpSta & Num, DnSta & Num=  ,2646.31, 2 ,3033.66, 2 , 0 , 0 , 0 ,,
       2       2
    27.8      42
       2       2
    27.8      42
BR Coef=-1 , 1 , 1 ,1.05, 0 ,,,.8,-1,1.2,0,
WSPro=,,,, 1 ,,,, 0 ,,,, 0 ,,,,-1 ,-1 ,-1 , 0 , 0 , 0 , 0 , 0
BC Design=,, 0 ,, 0 ,,,,,,

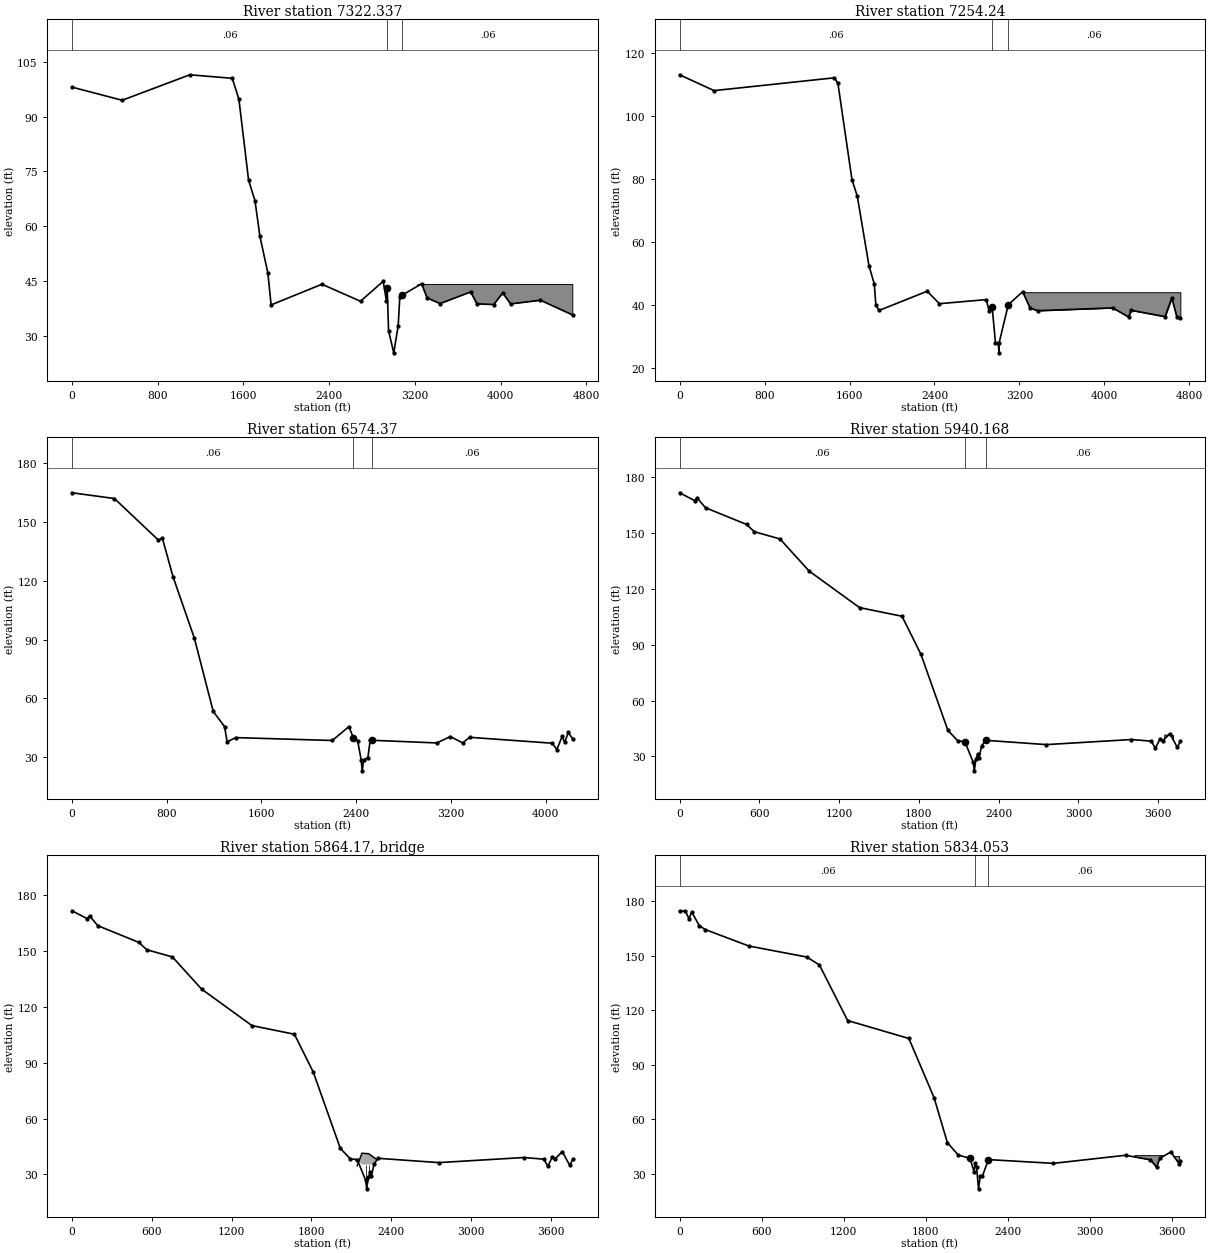
Type RM Length L Ch R = 1 ,7322.337,64.7,68.1,72.85
XS GIS Cut Line= 5
     3158098.051    13868846.127     3158230.793    13865935.262
     3158229.707    13865783.813     3158228.135    13865564.522
     3158288.949    13864178.065
#Sta/Elev= 30
       0   98.11  468.07   94.52 1099.52   101.5 1495.62  100.53 1557.74   94.76
 1647.84   72.62  1707.9   66.93 1753.68    57.2 1828.03   47.12 1858.06   38.42
 2332.62   44.08 2692.48   39.42 2903.87   44.89  2934.8   39.49 2941.53   43.17
 2954.15   31.35 3002.68   25.28 3044.16   32.74 3059.16    40.6 3083.73   41.14
 3262.46   44.22 3314.19   40.35 3434.46   38.77 3720.95   41.97 3779.26    38.7
 3936.49   38.51 4019.87   41.71 4093.52   38.68 4371.75    39.7 4672.43   35.65
#Mann= 3 ,-1 , 0
       0     .06       0 2941.53     .04       0 3083.73     .06       0
#Block Obstruct= 1 ,-1
 3228.06 4673.83      44
Bank Sta=2941.53,3083.73
XS Rating Curve= 0
Exp/Cntr=.5,.3

Type RM Length L Ch R = 1 ,7254.24 ,680.94,679.87,678.46
XS GIS Cut Line= 4
     3158168.389    13868851.538     3158292.468    13865951.769
     3158303.181    13865767.489     3158396.836    13864143.244
#Sta/Elev= 30
       0  113.02  324.57  107.99 1457.87  112.06 1490.78  110.28 1623.02   79.71
 1673.23   74.46 1782.77   52.47 1833.21    46.6 1848.23   39.83 1878.26   38.21
 2331.36   44.31 2446.11   40.35 2887.35   41.65 2914.21   38.04 2942.49   39.43
 2974.31   27.87 3000.56   27.93 3006.53   24.75 3007.64   27.81 3094.51   40.01
 3229.74   44.16 3300.08   38.95 3372.17   38.14 4078.28   39.03 4226.79   36.14
 4251.43   38.27 4570.54   36.26 4634.32   42.19 4682.15   36.08 4713.96   35.86
#Mann= 3 ,-1 , 0
       0     .06       0 2942.49     .04       0 3094.51     .06       0
#Block Obstruct= 1 ,-1
 3232.28    4715      44
Bank Sta=2942.49,3094.51
XS Rating Curve= 0
Exp/Cntr=.3,.1

Type RM Length L Ch R = 1 ,6574.37 ,634.09,634.2,634.32
XS GIS Cut Line= 6
     3158915.047    13868337.534     3158974.492    13865962.104
     3158979.997    13865805.391     3158980.677    13865786.009
     3158990.864    13865495.805     3159049.607    13864110.293
#Sta/Elev= 30
       0  164.93   357.9     162  728.88   140.8  762.77  141.81   852.8  122.11
 1032.86   90.76 1192.85   53.26 1287.94   45.55 1310.55   37.75 1382.22   39.92
 2198.24   38.44 2338.27   45.51 2376.17    39.9 2412.34   38.33 2441.58   28.64
 2451.03   22.94 2462.77   28.53 2498.75   29.69 2518.37   38.56 2532.98   38.55
  3080.8   37.18 3195.53   40.44 3298.97   37.23 3359.03   40.06 4055.57   37.05
 4094.69   33.83 4139.47   40.49 4161.39   37.52 4190.79   42.54 4229.52   39.18
#Mann= 3 ,-1 , 0
       0     .06       0 2376.17     .04       0 2532.98     .06       0
Bank Sta=2376.17,2532.98
XS Rating Curve= 0
Exp/Cntr=.5,.3

Type RM Length L Ch R = 1 ,5940.168,106.99,106.14,104.72
XS GIS Cut Line= 5
     3159515.619    13868121.112     3159608.749    13865967.938
     3159611.308    13865895.098     3159613.501    13865832.651
     3159615.145    13864356.994
#Sta/Elev= 30
       0   171.6  112.72  167.41  131.89  168.81     195  163.56   503.6  154.59
  561.66  150.69  755.17   146.8  973.91  129.57 1353.28  109.93 1672.67  105.28
 1814.79   84.89    2018   43.96 2093.07   38.35 2144.81   38.01 2208.45   26.81
  2216.2   22.26 2228.35   28.37 2243.31   31.49 2251.21   29.05 2271.36   35.71
 2303.21   38.65 2758.37   36.35 3398.21   39.08 3548.31   38.19 3578.27   34.33
 3613.22   39.53 3634.46   38.45 3686.95   42.25 3743.09   34.89 3766.22   38.08
#Mann= 3 ,-1 , 0
       0     .06       0 2144.81     .04       0 2303.21     .06       0
#Block Obstruct= 2 ,-1
                         3648.67 3708.97    41.5
Bank Sta=2144.81,2303.21
XS Rating Curve= 0
Exp/Cntr=.5,.3

Type RM Length L Ch R = 3 ,5864.17 ,,,
BEGIN DESCRIPTION:
BFI Bridge
END DESCRIPTION:
Bridge Culvert--1,0,-1,-1, 0
Deck Dist Width WeirC Skew NumUp NumDn MinLoCord MaxHiCord MaxSubmerge Is_Ogee
1,75,2.6,0, 4, 4, , , .95, 0, 0,0,,
 2144.81 2180.26 2231.25 2289.66
   34.68   41.39   41.12   38.15
   31.25   35.29   35.29   35.29
 2165.79 2174.16 2260.14 2304.67
    39.5   41.39   41.12   37.98
      35   35.29   35.29   35.29
Pier Skew, UpSta & Num, DnSta & Num=  ,2207.92, 2 ,2191.29, 2 , 0 , 0 , 0 ,,
     1.5     1.5
   27.76   47.76
     1.5     1.5
   27.76   47.76
Pier Skew, UpSta & Num, DnSta & Num=  ,2233.44, 2 ,2224.15, 2 , 0 , 0 , 0 ,,
     1.5     1.5
   27.76   47.76
     1.5     1.5
   27.76   47.76
BR Coef=-1 , 1 , 1 ,1.05, 0 ,,,.8,-1,1.2,0,
WSPro=,,,, 1 ,,,, 0 ,,,, 0 ,,,,-1 ,-1 ,-1 , 0 , 0 , 0 , 0 , 0
BC Design=,, 0 ,, 0 ,,,,,,

Type RM Length L Ch R = 1 ,5834.053,657.14,658.2,659.64
XS GIS Cut Line= 6
     3159677.936    13868094.059     3159715.621    13865989.346
     3159717.977    13865846.534     3159718.181    13865834.198
     3159718.389    13865821.575     3159737.107    13864430.866
#Sta/Elev= 30
       0  174.71   42.77  174.42   69.07  170.32    88.6  174.08  144.08  166.53
  186.99   164.4  507.13  155.32  930.74  149.26 1022.97  144.89 1229.31  114.32
 1677.29  104.47 1862.27   71.79 1959.37   47.07 2039.11   40.31  2124.4   38.53
  2154.4   31.09 2162.83   36.06 2173.11   33.62 2186.84   21.73 2199.41   28.63
 2214.41   28.55 2259.49   37.81 2734.41   35.75 3262.31    40.2  3444.8   37.68
 3489.76   33.69  3514.5    38.6 3594.54   42.05 3654.54   35.46 3663.68   37.32
#Mann= 3 ,-1 , 0
       0     .06       0 2162.83     .04       0 2259.49     .06       0
#Block Obstruct= 2 ,-1
                            3330 3650.78      40
Bank Sta=2124.4,2259.49
XS Rating Curve= 0
Exp/Cntr=.5,.3

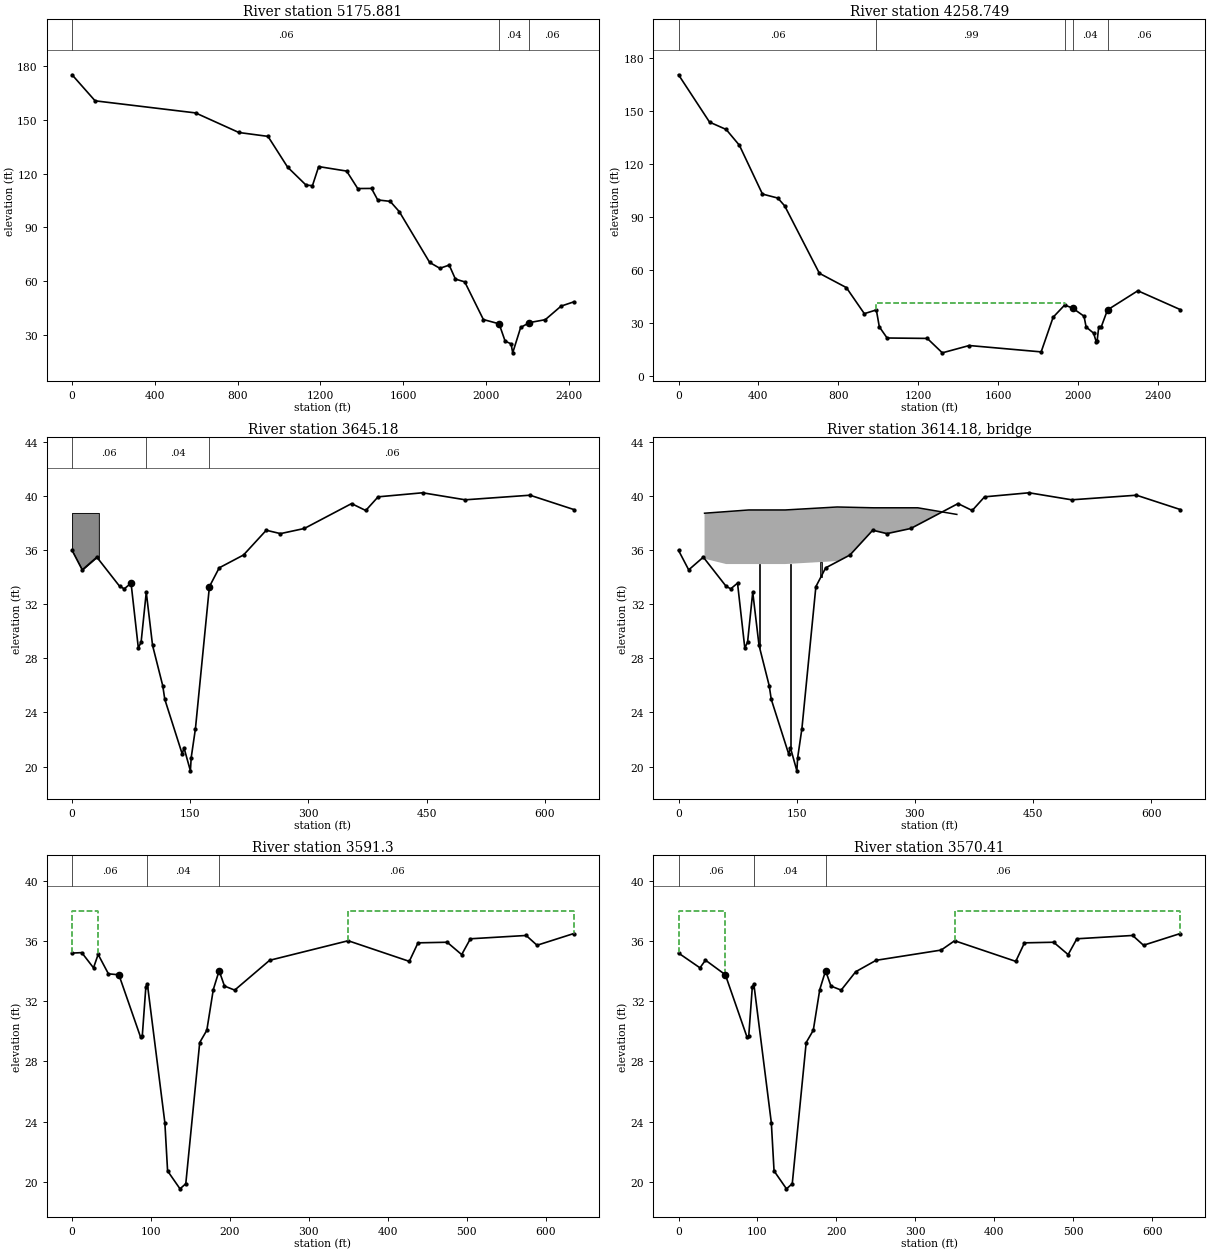
Type RM Length L Ch R = 1 ,5175.881,917.41,917.13,916.83
XS GIS Cut Line= 4
     3160283.919    13868045.364     3160370.997    13866027.447
     3160378.156    13865838.144     3160388.657    13865623.271
#Sta/Elev= 30
       0  175.06  111.24  160.55  596.64  153.81  805.89   142.9  946.52  140.74
 1041.33   123.6 1130.59  113.57 1161.44   113.3 1191.47  123.91  1326.6   121.4
 1380.06  111.68 1446.71  111.73 1476.74  105.32 1536.88  104.54  1580.8   98.82
 1727.77   70.49 1777.02   67.23 1822.06   69.02 1852.09   61.22 1897.13   59.67
 1987.21   38.68 2063.25    36.3 2092.29   26.64 2121.07   25.14  2128.9   20.13
 2167.35   34.26 2209.23   36.97 2286.19    38.6 2362.56   46.16 2424.36   48.55
#Mann= 3 ,-1 , 0
       0     .06       0 2063.25     .04       0 2209.23     .06       0
Bank Sta=2063.25,2209.23
XS Rating Curve= 0
Exp/Cntr=.3,.1

Type RM Length L Ch R = 1 ,4258.749,684.38,613.57,557.28
XS GIS Cut Line= 4
     3161219.947    13868039.953     3161287.966     13866059.79
     3161294.793    13865854.235     3161305.612    13865528.482
#Sta/Elev= 30
       0  170.46  155.32  143.67  238.47  139.52  304.72  130.58   420.2  102.96
  497.26  100.69  531.66   96.26  705.37   58.12  840.45   50.03   930.5   35.28
  990.54    37.4 1005.55   27.82 1044.44   21.51 1245.69   21.27 1321.03   13.11
 1455.81   17.25 1816.02   13.65 1876.06   33.28 1933.76   40.16 1973.42   38.44
 2030.63   33.83 2041.15   27.74 2078.83   24.23 2092.31   19.14  2096.4   20.01
 2104.15   27.57 2115.94    27.5 2148.32   37.41 2300.11   48.24 2512.93   37.57
#Mann= 5 ,-1 , 0
       0     .06       0  990.54     .99       0 1933.76     .06       0
 1973.42     .04       0 2148.32     .06       0
#XS Ineff= 1 ,-1
  990.54 1933.76    41.5
Permanent Ineff=
       T
Bank Sta=1973.42,2148.32
XS Rating Curve= 0
Exp/Cntr=.5,.3

Type RM Length L Ch R = 1 ,3645.18 ,33.4,32.75,32.2
XS GIS Cut Line= 4
     3161890.857     13865702.59     3161820.058    13865657.266
     3161709.042    13865583.031     3161360.378    13865349.884
#Sta/Elev= 30
       0   35.98   12.89   34.54   31.45   35.48   60.45   33.32   66.32   33.14
   74.89   33.56   84.13   28.76   87.66    29.2    94.2   32.89  102.18   28.96
  115.13   25.97  117.71   24.97  139.81   20.93  142.11   21.38  150.23   19.68
  151.23   20.65  156.63    22.8  174.36    33.3  186.79   34.69  217.67   35.64
  246.54   37.47  264.58   37.22  294.87    37.6   354.8   39.44  372.85   38.93
  388.52   39.94  445.03   40.24  499.16   39.72  581.39   40.06  637.05      39
#Mann= 3 ,-1 , 0
       0     .06       0    94.2     .04       0  174.36     .06       0
#Block Obstruct= 2 , 0
       0      34   38.75  581.39       0    41.5
Bank Sta=74.89,174.36
XS Rating Curve= 0
Exp/Cntr=.5,.3

Type RM Length L Ch R = 3 ,3614.18 ,,,
BEGIN DESCRIPTION:
Rail Road Bridge
END DESCRIPTION:
Bridge Culvert--1,0,-1,-1, 0
Deck Dist Width WeirC Skew NumUp NumDn MinLoCord MaxHiCord MaxSubmerge Is_Ogee
1,30,2.6,0, 7, 7, , , .95, 0, 0,0,,
   33.02   89.15  135.38  201.42  247.64  303.77   353.3
   38.73   38.97   38.97   39.19   39.13   39.13   38.64
   34.97   34.97   34.97   35.19   35.13   35.13   35.13
   33.02   89.15  135.38  201.42  247.64  303.77   353.3
   38.73   38.97   38.97   39.19   39.13   39.13   38.64
   34.97   34.97   34.97   35.19   35.13   35.13   35.13
Pier Skew, UpSta & Num, DnSta & Num=  ,103.17, 2 ,103.17, 2 , 0 , 0 , 0 ,,
     1.5     1.5
   27.76   35.19
     1.5     1.5
   23.43   35.19
Pier Skew, UpSta & Num, DnSta & Num=  ,141.98, 2 ,141.98, 2 , 0 , 0 , 0 ,,
     1.5     1.5
   27.76   35.19
     1.5     1.5
   23.43   35.19
Pier Skew, UpSta & Num, DnSta & Num=  ,180.79, 2 ,180.79, 2 , 0 , 0 , 0 ,,
     1.5     1.5
   27.76   35.19
     1.5     1.5
   23.43   35.19
BR Coef=-1 , 1 , 1 ,1.05, 0 ,,,.8,-1,1.2,0,
WSPro=,,,, 1 ,,,, 0 ,,,, 0 ,,,,-1 ,-1 ,-1 , 0 , 0 , 0 , 0 , 0
BC Design=,, 0 ,, 0 ,,,,,,

Type RM Length L Ch R = 1 ,3591.3  ,21.2,22.88,26.34
XS GIS Cut Line= 4
      3161956.51     13865642.14      3161845.64     13865582.08
      3161608.68      13865453.7      3161246.56     13865257.56
#Sta/Elev= 30
       0   35.19   12.29   35.22   27.15   34.21   33.02    35.1   46.04   33.81
    59.3   33.75   86.74   29.61    88.9   29.66   93.47   32.96   95.42   33.12
  117.53   23.92  120.98   20.72  136.71   19.53  144.04   19.87  161.68   29.25
  170.66   30.06  178.89   32.77  186.26   34.02  193.02      33  205.99   32.73
  250.21   34.71  349.71   36.01  427.12   34.64  438.17   35.87  475.06   35.91
  493.46   35.09  504.51   36.14  575.13   36.36  588.91   35.71  635.55   36.49
#Mann= 3 ,-1 , 0
       0     .06       0   95.42     .04       0  186.26     .06       0
#XS Ineff= 2 , 0
       0   33.02      38  349.71       0      38
Permanent Ineff=
       T       T
Bank Sta=59.3,186.26
XS Rating Curve= 0
Exp/Cntr=.5,.3

Type RM Length L Ch R = 1 ,3570.41 ,19.94,20.89,25.31
XS GIS Cut Line= 4
      3161951.45     13865620.12      3161862.93     13865572.89
      3161689.59     13865477.76      3161294.01     13865269.37
#Sta/Elev= 30
       0   35.19   27.15   34.21   34.13   34.72    59.3   33.75   86.74   29.61
    88.9   29.66   93.47   32.96   95.42   33.12  117.53   23.92  120.98   20.72
  136.71   19.53  144.04   19.87  161.68   29.25  170.66   30.06  178.89   32.77
  186.26   34.02  193.02      33  205.99   32.73  224.36   33.95  250.21   34.71
  332.65   35.39  349.71   36.01  427.12   34.64  438.17   35.87  475.06   35.91
  493.46   35.09  504.51   36.14  575.13   36.36  588.91   35.71  635.55   36.49
#Mann= 3 ,-1 , 0
       0     .06       0   95.42     .04       0  186.26     .06       0
#XS Ineff= 2 , 0
       0    59.3      38  349.71       0      38
Permanent Ineff=
       T       T
Bank Sta=59.3,186.26
XS Rating Curve= 0
Exp/Cntr=.5,.3

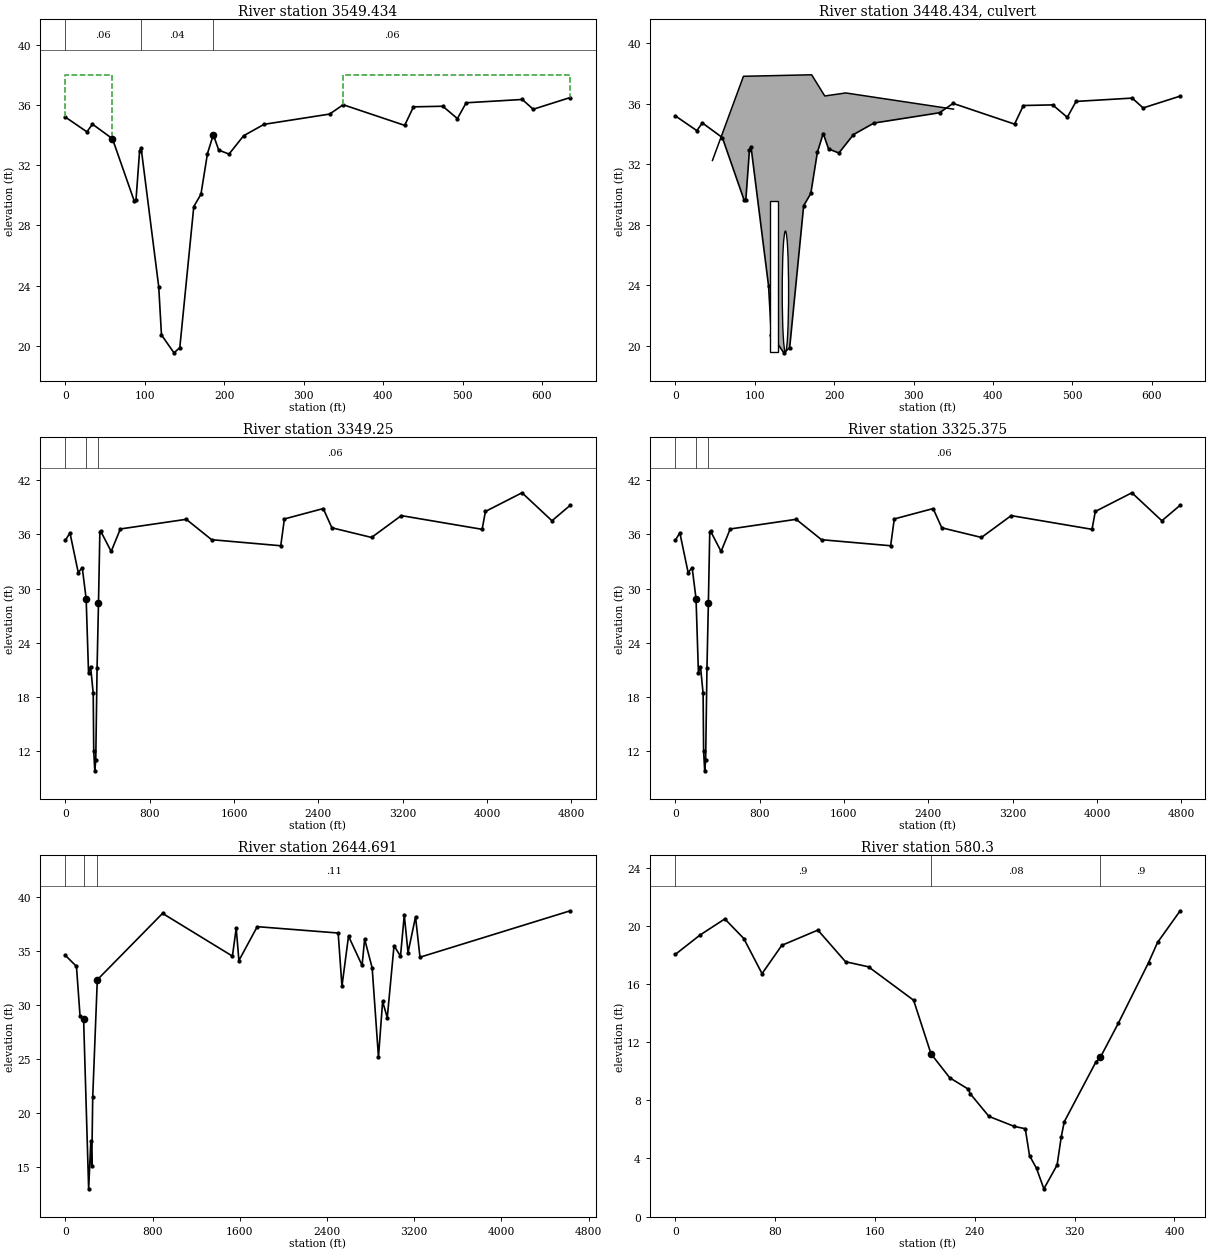
Type RM Length L Ch R = 1 ,3549.434,221,224,226.71
XS GIS Cut Line= 4
     3161950.373    13865605.199     3161895.788    13865584.437
     3161757.407    13865508.995     3161389.051    13865308.178
#Sta/Elev= 30
       0   35.19   27.15   34.21   34.13   34.72    59.3   33.75   86.74   29.61
    88.9   29.66   93.47   32.96   95.42   33.12  117.53   23.92  120.98   20.72
  136.71   19.53  144.04   19.87  161.68   29.25  170.66   30.06  178.89   32.77
  186.26   34.02  193.02      33  205.99   32.73  224.36   33.95  250.21   34.71
  332.65   35.39  349.71   36.01  427.12   34.64  438.17   35.87  475.06   35.91
  493.46   35.09  504.51   36.14  575.13   36.36  588.91   35.71  635.55   36.49
#Mann= 3 ,-1 , 0
       0     .06       0   95.42     .04       0  186.26     .06       0
#XS Ineff= 2 , 0
       0    59.3      38  349.71       0      38
Permanent Ineff=
       T       T
Bank Sta=59.3,186.26
XS Rating Curve= 0
Exp/Cntr=.5,.3

Type RM Length L Ch R = 2 ,3448.434,,,
BEGIN DESCRIPTION:
Highway 90
END DESCRIPTION:
Bridge Culvert--1,0,-1,-1, 0
Deck Dist Width WeirC Skew NumUp NumDn MinLoCord MaxHiCord MaxSubmerge Is_Ogee
1,100,2.6,0, 6, 6, , , .95, 0, 0,0,,
   46.85   85.85   171.7  188.21  214.62  350.21
   32.24    37.8    37.9    36.5    36.7   35.63
                                                
   46.85   85.85   171.7  188.21  214.62  350.21
   32.24    37.8    37.9    37.5    37.5   35.63
                                                
Culvert=2,10,10,100,.013,.4,1,8,1,19.57,124.43,9.8,275,Culvert #1  , 0 ,.05
Culvert Bottom n=.013
Culvert=1,8,,100,.013,.5,1,1,1,19.57,138.68,9.8,288.52,Culvert #2  , 0 ,.05
Culvert Bottom n=.013
BC Design=,, 0 ,, 0 ,,,,,,

Type RM Length L Ch R = 1 ,3349.25 ,23.875,23.875,23.875
XS GIS Cut Line= 4
      3162169.93     13865610.29      3161939.05     13865486.39
      3161820.29     13865422.83      3157624.07     13863173.12
#Sta/Elev= 30
       0   35.33   43.74   36.17  122.36   31.77  160.44   32.31  197.37   28.86
     220   20.66  239.47   21.35  264.31    18.4  269.25      12  279.37     9.8
  288.42      11  300.98   21.21  314.46   28.42  327.39   36.24  335.56   36.35
  434.66   34.11   521.8    36.6 1147.21   37.67 1387.89   35.41 2043.42   34.74
 2077.93   37.71 2446.62   38.86 2528.43   36.73 2904.97   35.66 3187.17   38.08
 3953.86   36.56 3984.95   38.54 4332.02   40.61  4616.4   37.51 4790.08   39.23
#Mann= 3 ,-1 , 0
       0     .06       0  197.37     .04       0  314.46     .06       0
Bank Sta=197.37,314.46
XS Rating Curve= 0
Exp/Cntr=.5,.3

Type RM Length L Ch R = 1 ,3325.375,681.69,681.69,681.69
XS GIS Cut Line= 4
     3162188.438    13865491.578     3162005.586    13865392.256
     3161883.317    13865322.154     3158021.723     13863128.75
#Sta/Elev= 30
       0   35.33   43.74   36.17  122.36   31.77  160.44   32.31  197.37   28.86
     220   20.66  239.47   21.35  264.31    18.4  269.25      12  279.37     9.8
  288.42      11  300.98   21.21  314.46   28.42  327.39   36.24  335.56   36.35
  434.66   34.11   521.8    36.6 1147.21   37.67 1387.89   35.41 2043.42   34.74
 2077.93   37.71 2446.62   38.86 2528.43   36.73 2904.97   35.66 3187.17   38.08
 3953.86   36.56 3984.95   38.54 4332.02   40.61  4616.4   37.51 4790.08   39.23
#Mann= 3 ,-1 , 0
       0     .06       0  197.37     .04       0  314.46     .06       0
Bank Sta=197.37,314.46
XS Rating Curve= 0
Exp/Cntr=.3,.1

Type RM Length L Ch R = 1 ,2644.691,2038.45,2041.38,2059.4
XS GIS Cut Line= 4
     3162567.178     13865031.68     3162426.634     13864961.11
     3162310.304    13864895.579     3158551.281    13862725.277
#Sta/Elev= 30
       0   34.58  101.97   33.56  134.93   28.94  167.33    28.7  213.77   12.96
  233.75   17.36  242.16    15.1  250.96   21.43  293.07   32.32  891.58   38.47
 1532.44   34.51 1567.08    37.1 1591.93    34.1 1759.92   37.24 2502.39   36.65
 2537.04   31.72 2597.19   36.36 2721.86   33.65 2744.88   36.09 2814.16   33.42
 2871.91   25.16 2909.99   30.31 2952.73   28.81 3014.66   35.48 3073.97    34.5
 3108.61   38.31 3143.25   34.84 3211.91   38.15 3252.72   34.41 4631.34   38.71
#Mann= 3 ,-1 , 0
       0      .9       0  167.33     .08       0  293.07     .11       0
Bank Sta=167.33,293.07
XS Rating Curve= 0
Exp/Cntr=.3,.1

Type RM Length L Ch R = 1 ,580.3   ,3.87,0,.1
XS GIS Cut Line= 4
     3163304.949    13863639.913     3163305.769    13863500.538
     3163306.946    13863300.322     3163308.425    13863235.372
#Sta/Elev= 29
       0   18.05   19.87   19.39   39.73    20.5   54.91   19.15   69.56   16.73
   85.37   18.68  114.29   19.73  136.46   17.55  154.85    17.2  190.99    14.9
  204.92   11.21  219.92    9.56  234.92    8.77  236.26    8.47  251.34     6.9
  271.64    6.21  280.46    6.05  283.85     4.2  289.47    3.32  295.35    1.91
  305.95    3.55  309.26    5.48   311.7    6.53  336.87   10.62  340.64   10.97
  354.92    13.3  379.23   17.49  386.44   18.88  404.56   21.06
#Mann= 3 ,-1 , 0
       0      .9       0  204.92     .08       0  340.64      .9       0
Bank Sta=204.92,340.64
XS Rating Curve= 0
Exp/Cntr=.3,.1

Chan Stop Cuts=-1